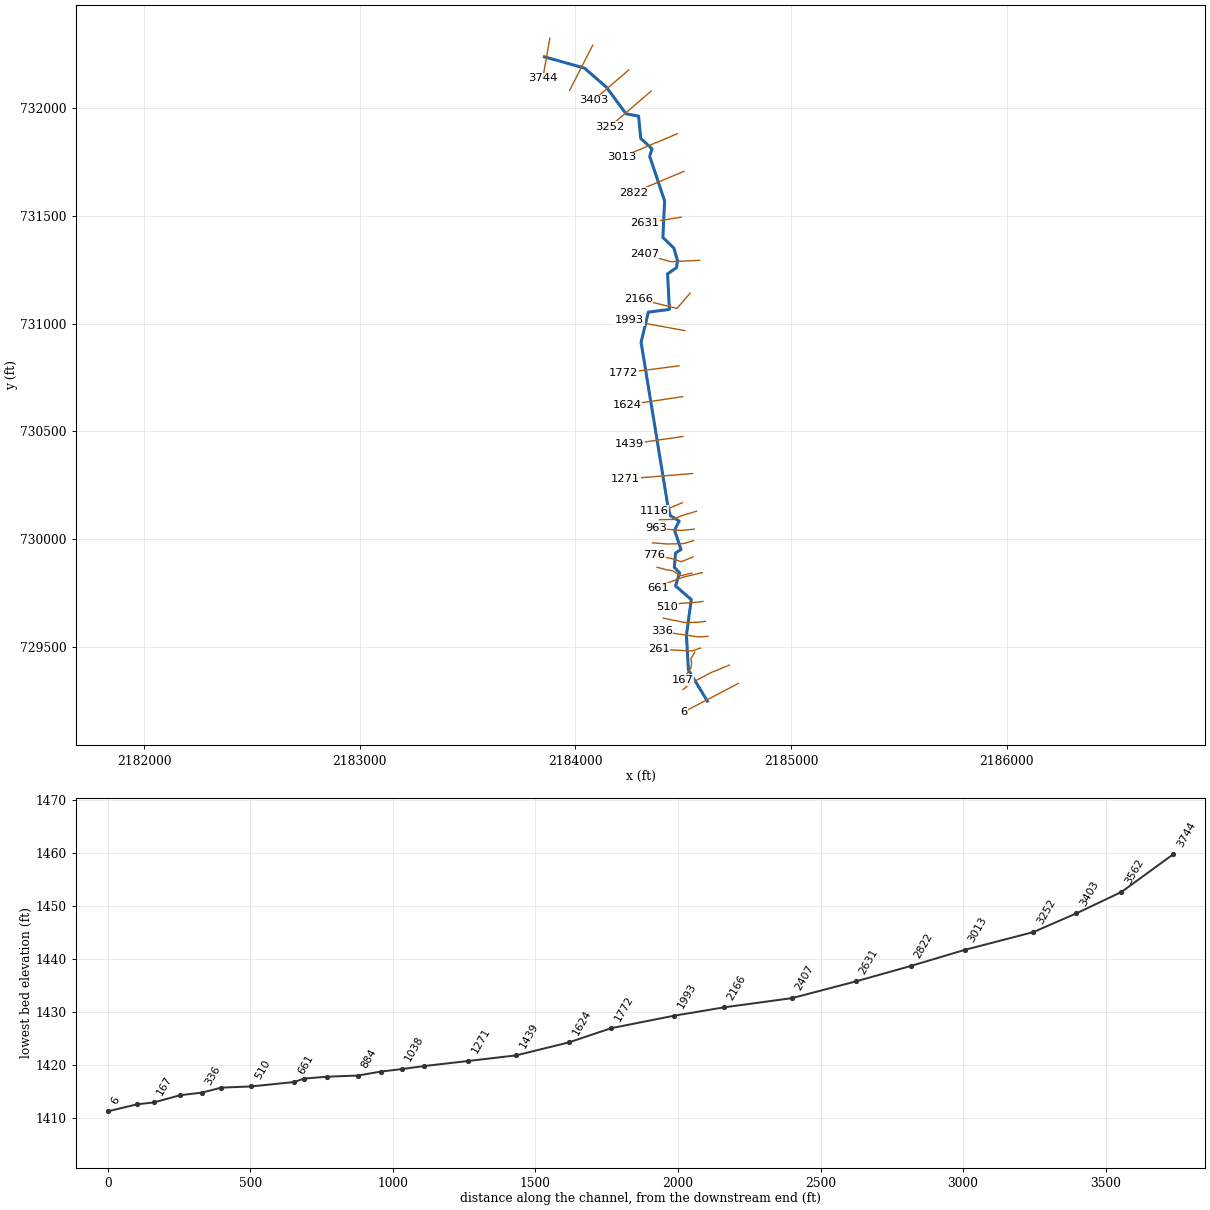
--- FINKRNT2.prj (project) ---

Proj Title=FINKRNT2
Current Plan=p01
Default Exp/Contr=0,0
English Units
Geom File=g01
Flow File=f01
Plan File=p01
BEGIN DESCRIPTION:
---------- MODELED AS PART OF WVEMD CTP PROGRAM, 2023----------
Stream Name: Fink Run Tributary 2
Flood Zone:  AFH
Upshur County, WV
HEC-RAS Version: RAS 6.3
Vertical Datum: NAVD88
Projection: NAD 1983 StatePlane West Virginia S FIPS 4702 (US Feet)
Terrain: 1-meter LIDAR (FEMA Region III 3DEP collected 2016-2018)
Land Use: 2019 NLCD
Hydrologic Method:
WV SIR2010-5033 regression equations
Additional Model Notes:
None
END DESCRIPTION:
DSS Export Rating Curves= 0
DSS Export Rating Curve Sorted= 0
DSS Export Volume Flow Curves= 0
DXF OffsetX= 0
DXF OffsetY= 0
DXF ScaleX= 0
DXF ScaleY= 0

--- FINKRNT2.p01 (plan) ---

Plan Title=Floodplain
Program Version=6.30
Short Identifier=Floodplain
Geom File=g01
Flow File=f01
Subcritical Flow
K Sum by GR= 0
Std Step Tol= 0.01
Critical Tol= 0.01
Num of Std Step Trials= 20
Max Error Tol= 0.3
Flow Tol Ratio= 0.001
Split Flow NTrial= 30
Split Flow Tol= 0.02
Split Flow Ratio= 0.02
Log Output Level= 0
Friction Slope Method= 1
Unsteady Friction Slope Method= 2
Unsteady Bridges Friction Slope Method= 1
Parabolic Critical Depth
Global Vel Dist= 0 , 0 , 0
Global Log Level= 0
CheckData=True
Encroach Param=-1 ,0,0, 0
Computation Interval=1MIN
Output Interval=1HOUR
Instantaneous Interval=1HOUR
Mapping Interval=1HOUR
Computation Time Step Use Courant=        0
Computation Time Step Use Time Series=    0
Computation Time Step Count To Double=0
Computation Time Step Max Doubling=0
Computation Time Step Max Halving=0
Computation Time Step Residence Courant=0
Run HTab= 0
Run UNet= 0
Run Sediment= 0
Run PostProcess= 0
Run WQNet= 0
Run RASMapper=-1
UNET Theta= 1
UNET Theta Warmup= 1
UNET ZTol= 0.02
UNET ZSATol= 0.02
UNET MxIter= 20
UNET Max Iter WO Improvement= 0
UNET MaxInSteps= 0
UNET DtIC= 0
UNET DtMin= 0
UNET MaxCRTS= 20
UNET WFStab= 2
UNET SFStab= 1
UNET WFX= 1
UNET SFX= 1
UNET Gravity=32.17405
UNET 1D Methodology=Finite Difference
UNET DSS MLevel= 4
UNET Pardiso=0
UNET DZMax Abort= 100
UNET Use Existing IB Tables=-1
UNET Froude Reduction=False
UNET Froude Limit= 0.8
UNET Froude Power= 4
UNET D1 Cores= 0
UNET WindReference=Eulerian
UNET WindDragFormulation=Hsu (1988)
UNET D2 Coriolis=0
UNET D2 Cores= 0
UNET D2 Theta= 1
UNET D2 Theta Warmup= 1
UNET D2 Z Tol= 0.01
UNET D2 Volume Tol= 0.01
UNET D2 Max Iterations= 20
UNET D2 Equation= 0
UNET D2 RampUpFraction=0.1
UNET D2 TimeSlices= 1
UNET D2 Turbulence Formulation=None
UNET D2 Eddy Viscosity=0.3
UNET D2 Transverse Eddy Viscosity=0.1
UNET D2 Smagorinsky Mixing=0.05
UNET D2 BCVolumeCheck=0
UNET D2 Cores=0
UNET D2 SolverType=PARDISO (Direct)
UNET D2 Minimum Iterations= 3
UNET D2 Maximum Iterations= 30
UNET D2 Restart Number= 10
UNET D2 Relaxation Coeff=1.3
UNET D2 SOR Precondition Iterations= 10
UNET D2 ILUT Maximum Fill= 8
UNET D2 ILUT Tolerance=1E-08
UNET D2 Convergence Tolerance=0.00001
UNET D1D2 MaxIter= 0
UNET D1D2 ZTol=0.01
UNET D1D2 QTol=0.1
UNET D1D2 MinQTol=1
Write IC File= 0
Write IC File at Fixed DateTime=0
Write IC File at Sim End=0
Echo Input=False
Echo Parameters=False
Echo Output=False
Write Detailed= 0
HDF Write Warmup=0
HDF Write Time Slices=0
HDF Flush=0
HDF Compression= 1
HDF Chunk Size= 1
HDF Spatial Parts= 1
HDF Use Max Rows=0
HDF Fixed Rows= 1
Calibration Method= 0
Calibration Iterations= 20
Calibration Max Change=0.05
Calibration Tolerance=0.2
Calibration Maximum=1.5
Calibration Minimum=0.5
Calibration Optimization Method= 1
WQ AD Non Conservative
WQ ULTIMATE=-1
WQ Max Comp Step=1HOUR
WQ Output Interval=15MIN
WQ Output Selected Increments= 0
WQ Output face flow=0
WQ Output face velocity=0
WQ Output face area=0
WQ Output face dispersion=0
WQ Output cell volume=0
WQ Output cell surface area=0
WQ Output cell continuity=0
WQ Output cumulative cell continuity=0
WQ Output face conc=0
WQ Output face dconc_dx=0
WQ Output face courant=0
WQ Output face peclet=0
WQ Output face adv mass=0
WQ Output face disp mass=0
WQ Output cell mass=0
WQ Output cell source sink temp=0
WQ Output nsm pathways=0
WQ Output nsm derived pathways=0
WQ Create Restart=0
WQ Fixed Restart=0
WQ System Summary=0
WQ Write To DSS=0
Sorting and Armoring Iterations= 10
XS Update Threshold= 0.02
Bed Roughness Predictor= 0
Hydraulics Update Threshold= 0.02
Energy Slope Method= 1
Volume Change Method= 1
Sediment Retention Method= 0
Sediment TS Multiplier= 1
Warm Up Method= 0
XS Weighting Method= 0
Number of US Weighted Cross Sections= 1
Number of DS Weighted Cross Sections= 1
Upstream XS Weight=0
Main XS Weight=1
Downstream XS Weight=0
Number of DS XS's Weighted with US Boundary= 1
Upstream Boundary Weight= 1
Weight of XSs Associated with US Boundary= 0
Number of US XS's Weighted with DS Boundary= 1
Downstream Boundary Weight= 0.5
Weight of XSs Associated with DS Boundary= 0.5
Percentile Method= 0
Sediment Output Level= 3
Mass or Volume Output= 0
Output Increment Type= 1
Profile and TS Output Increment= 1
Transport Output Increment 1
XS Output Flag= 0
XS Output Increment= 10
Read HDF5 Sediment Hotstart= 0
Sediment Hotstart Type= 0
Write Gradation File= 0
Read Gradation Hotstart= 0
Write HDF5 File= 1
Write Binary Output= 1
Write DSS Sediment File= 0
DSS Sediment Output Type= 1
SV Curve= 0
Specific Gage Flag= 0
Subcell Erosion Methods= 0
Subcell Deposition Methods= 0
Advection Scheme= 1
Matrix Solver= 0
Implicit Weighting Factor= 1
Maximum Outer Loop Convergence Iterations= 5
Convergence Maximum Absolute= 0.001
Convergence RMSE= 0.0001
Grain Fractions Max Abs Error= 0.001
Max Subgrid Regions= 1
Max Subgrid Length Scale= 3.402823E+38
Initial Layer Thickness= 3.402823E+38
Min Layer Thickness= 3.402823E+38
Max Layer Thickness= 3.402823E+38
Number of Layers= 5

--- FINKRNT2.f01 (steady flow) ---

Flow Title=Flow
Program Version=6.30
Number of Profiles= 1
Profile Names=01pct
River Rch & RM=FINKRNT2,Main            ,3744
    61.3
River Rch & RM=FINKRNT2,Main            ,1624
    87.7
River Rch & RM=FINKRNT2,Main            ,1439
    97.6
River Rch & RM=FINKRNT2,Main            ,776
     120
Boundary for River Rch & Prof#=FINKRNT2,Main            , 1
Up Type= 0
Dn Type= 3
Dn Slope=0.01185
DSS Import GetInterval= 0
DSS Import GetPeak= 0
DSS Import FillOption= 0

--- FINKRNT2.g01 (geometry) ---

Geom Title=Geometry
Program Version=6.30

River Reach=FINKRNT2        ,Main
Reach XY= 30
2183856.13195484732237.6860680232184041.73274191732185.128115222
2184143.80996583732096.3029444862184234.51527988731973.012164785
2184292.56295474731962.5432014372184302.46501598731859.273602358
2184354.78139699731810.7869229862184344.05405118731775.808658387
 2184413.3085777731568.3935516922184405.20718254731399.609658435
2184456.01682563 731350.164329352184472.98874888731292.389273585
2184468.83422923731259.8521701672184427.01700689 731230.37054622
2184435.48614914731065.5710790162184337.72398064731052.809916003
2184304.21646179730912.7081785832184427.78751439730156.736818314
2184439.23442036730108.9108873462184480.83976802730083.305518135
2184459.16472629730040.9331232462184489.40237854729951.359636918
2184464.02663563729934.8358973712184458.29077944729868.978482679
2184482.54616418729843.1651398242184464.23637389729781.964163259
2184536.88922569729719.0514128952184514.43115518 729552.19935298
2184523.79590747 729392.135900842184611.70200001729247.604000002

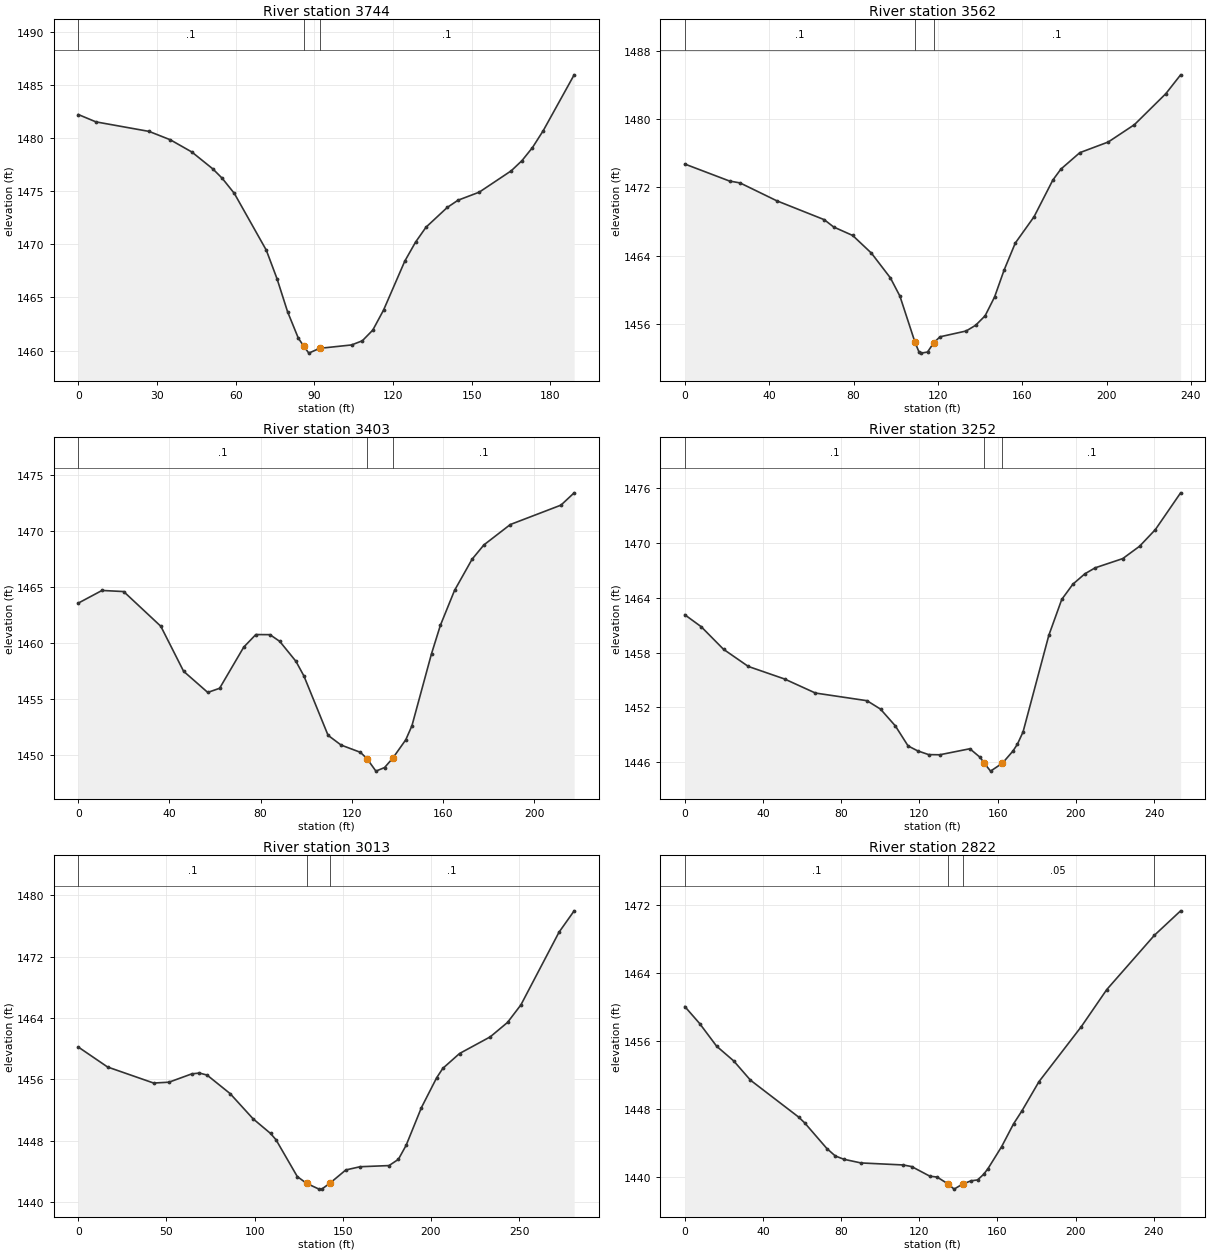
Type RM Length L Ch R = 1 ,3744    ,182.4,182.4,179.4
XS GIS Cut Line= 2
2183881.19921814732323.7883162952183848.40397098732137.595945294
#Sta/Elev= 30
       0 1482.23     6.7 1481.54      27 1480.64    35.1 1479.85    43.3  1478.7
    51.3 1477.11    54.9 1476.22    59.5  1474.8    71.7 1469.45    75.8 1466.75
    79.8 1463.66    83.9 1461.17      86 1460.41    87.9 1459.76      92 1460.21
   104.2 1460.53   108.3 1460.92   112.3 1461.93   116.4 1463.81   124.5 1468.42
   128.6 1470.21   132.6 1471.62   140.7 1473.48   144.8 1474.16   152.9 1474.92
   165.1 1476.93   169.2 1477.89   173.2 1479.12   177.3 1480.71   189.1 1485.97
#Mann= 3 ,-1,0
       0      .1       0      86    .045       0      92      .1       0
Bank Sta=86,92
XS Rating Curve= 0 ,0
Exp/Cntr(USF)=0,0
Exp/Cntr=0.3,0.1

Type RM Length L Ch R = 1 ,3562    ,159.7,158.5,155.8
XS GIS Cut Line= 2
2184080.08652353732292.0509803292183973.23749244732082.584562953
#Sta/Elev= 30
       0 1474.74    21.2 1472.75    26.2 1472.53    43.6 1470.44    66.1 1468.23
    70.6 1467.37    79.6 1466.38    88.5 1464.31    97.5 1461.41     102 1459.28
   109.1 1453.92     111 1452.77   112.1 1452.61   115.1 1452.74     118 1453.81
     121 1454.52   133.4  1455.2   137.9 1455.87   142.4 1456.98   146.9 1459.19
   151.4 1462.33   156.7 1465.49   165.6 1468.57   174.5 1472.86   178.3 1474.14
   187.3 1476.07   200.8 1477.32   213.2 1479.35   228.1 1482.98   235.1 1485.18
#Mann= 3 ,-1,0
       0      .1       0   109.1    .045       0     118      .1       0
Bank Sta=109.1,118
XS Rating Curve= 0 ,0
Exp/Cntr(USF)=0,0
Exp/Cntr=0.3,0.1

Type RM Length L Ch R = 1 ,3403    ,149.2,150.7,148.2
XS GIS Cut Line= 2
2184247.23649295732176.7386596522184082.20234593732034.978559003
#Sta/Elev= 30
       0 1463.57    10.4  1464.7    19.9  1464.6    36.2  1461.5    46.2 1457.48
    56.8 1455.59      62 1455.96    72.6 1459.64    77.9 1460.76    84.1 1460.75
    88.4 1460.15    95.5 1458.37      99 1457.06   109.6 1451.76   115.3 1450.89
   123.8 1450.24   126.7 1449.67   130.6 1448.56   134.4 1448.88     138 1449.72
   143.7 1451.36   146.4 1452.61     155 1459.05   158.9 1461.59   165.1  1464.7
   172.8 1467.49     178 1468.77   189.6 1470.59   211.8 1472.32   217.6 1473.42
#Mann= 3 ,-1,0
       0      .1       0   126.7    .045       0     138      .1       0
Bank Sta=126.7,138
XS Rating Curve= 0 ,0
Exp/Cntr(USF)=0,0
Exp/Cntr=0.3,0.1

Type RM Length L Ch R = 1 ,3252    ,236.8,239.2,232.2
XS GIS Cut Line= 2
2184350.91179044732078.3529181572184158.37195225731913.318771133
#Sta/Elev= 30
       0 1462.15     8.4 1460.84    19.8 1458.37    32.5 1456.49      51 1455.12
    66.8 1453.58    93.2 1452.74   100.1 1451.82   107.7 1449.98   114.2 1447.79
   119.1 1447.25   124.7 1446.84   130.4 1446.82   145.8 1447.48   151.1 1446.53
   153.1 1445.91   156.4 1445.03  162.471445.902   167.8 1447.22   170.1 1447.97
     173 1449.32   186.2 1459.91   192.8 1463.83   198.5  1465.5   204.6 1466.63
   209.9 1467.29     224  1468.3   232.6 1469.65   240.7 1471.48   253.6  1475.5
#Mann= 3 ,-1,0
       0      .1       0   153.1    .045       0  162.47      .1       0
Bank Sta=153.1,162.47
XS Rating Curve= 0 ,0
Exp/Cntr(USF)=0,0
Exp/Cntr=0.3,0.1

Type RM Length L Ch R = 1 ,3013    ,190.2,191.2,189.2
XS GIS Cut Line= 2
2184471.51366711731880.5235239682184212.32542339731771.558670485
#Sta/Elev= 30
       0 1460.21    16.6 1457.61    42.7 1455.52    51.4 1455.63    64.4 1456.72
    68.7 1456.82      73 1456.56    86.1 1454.14    99.1 1450.86     109 1448.95
   112.1 1448.13   124.2 1443.32   129.5 1442.44   136.5 1441.69   138.1  1441.7
   142.5 1442.43   151.7 1444.19   159.8 1444.61   176.2 1444.76   181.5 1445.57
   185.9  1447.4   194.6 1452.33   203.2  1456.2   206.7 1457.43   216.2 1459.37
   233.6 1461.54   243.4 1463.42     251 1465.71   272.6 1475.18   281.2 1477.97
#Mann= 3 ,-1,0
       0      .1       0   129.5    .045       0   142.5      .1       0
Bank Sta=129.5,142.5
XS Rating Curve= 0 ,0
Exp/Cntr(USF)=0,0
Exp/Cntr=0.3,0.1

Type RM Length L Ch R = 1 ,2822    ,191.3,191.6,189.4
XS GIS Cut Line= 2
2184503.17863051731706.3954922222184269.38025556731608.009750727
#Sta/Elev= 30
       0 1460.09     7.6 1458.09    16.3 1455.42      25  1453.7    33.6 1451.43
    58.2  1447.1    61.3 1446.42    72.7 1443.39      77 1442.52    81.4 1442.13
    90.1  1441.7   111.8 1441.46   116.1 1441.27   125.4 1440.14   129.1 1440.04
   134.9  1439.2   137.8 1438.62   142.1 1439.21   146.5  1439.6   149.8  1439.7
   152.9 1440.36   155.1 1441.02   162.1 1443.61   168.2 1446.29   172.5 1447.82
   181.2 1451.25   202.9 1457.73   215.9 1462.08   240.3 1468.47   253.7 1471.34
#Mann= 4 ,-1,0
       0      .1       0   134.9    .045       0   142.1     .05       0
     240      .1       0
Bank Sta=134.9,142.1
XS Rating Curve= 0 ,0
Exp/Cntr(USF)=0,0
Exp/Cntr=0.3,0.1

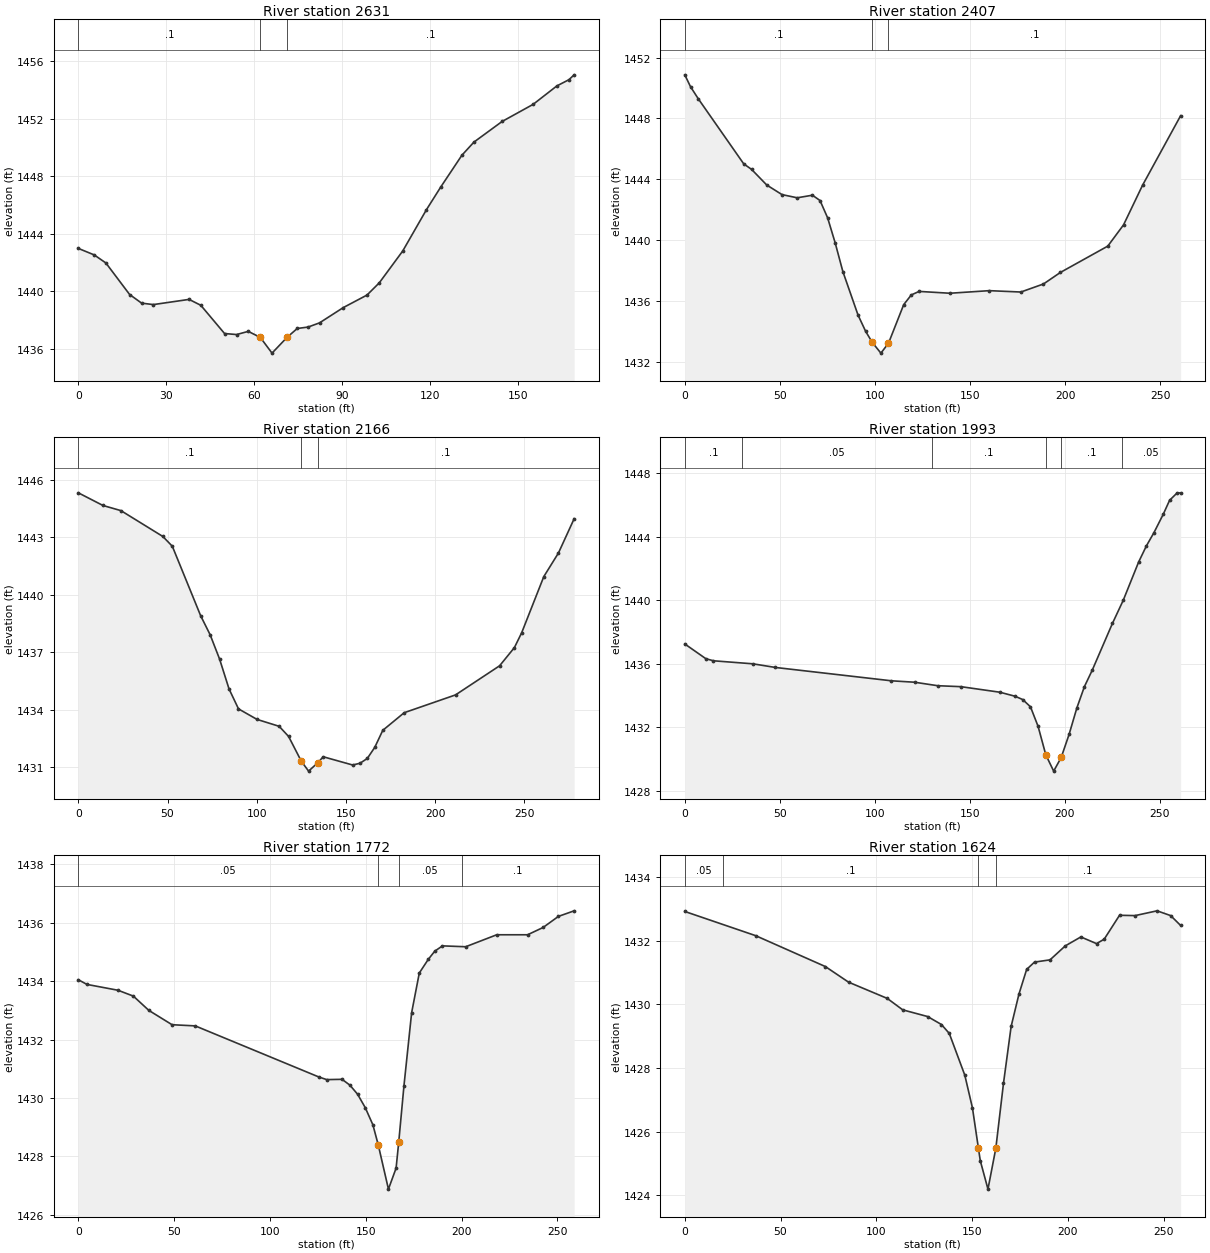
Type RM Length L Ch R = 1 ,2631    ,222.9,223.8,222.3
XS GIS Cut Line= 2
2184489.49815749731493.3280251822184322.34818807 731466.88024521
#Sta/Elev= 30
       0 1442.99     5.4 1442.54     9.4 1441.98    17.5 1439.79    21.6 1439.19
    25.6 1439.09    37.8 1439.45    41.8 1439.04    49.9 1437.08      54 1437.01
      58 1437.23    62.1 1436.81    66.1 1435.72    71.2 1436.81    74.7 1437.43
    78.4 1437.53    82.3 1437.82    90.4 1438.88    98.5 1439.75   102.7  1440.6
   110.7 1442.81   118.8 1445.68   123.7 1447.26   130.9 1449.46     135 1450.37
   144.6  1451.8   155.2 1452.99   163.3 1454.27   167.4  1454.7   169.2 1455.04
#Mann= 3 ,-1,0
       0      .1       0    62.1    .045       0    71.2      .1       0
Bank Sta=62.1,71.2
XS Rating Curve= 0 ,0
Exp/Cntr(USF)=0,0
Exp/Cntr=0.3,0.1

Type RM Length L Ch R = 1 ,2407    ,239.6,240.5,236.5
XS GIS Cut Line= 3
 2184575.1889646731293.3828085952184441.89215354731287.035341402
2184319.17445447731320.888499766
#Sta/Elev= 30
       0 1450.87       3 1450.09       7 1449.31      31 1445.01    35.1 1444.65
    43.1 1443.62    51.1 1442.99    59.1 1442.78    67.1 1442.95    71.1  1442.6
    75.1 1441.46    79.1  1439.8    83.1 1437.93    91.1 1435.06    95.1 1433.99
    98.6 1433.26   103.1 1432.56   107.1 1433.21   115.1 1435.75   119.1 1436.39
   123.2 1436.62   139.4  1436.5   160.1 1436.67   176.7 1436.58   188.6 1437.11
   197.5 1437.87   222.4  1439.6   230.7    1441   240.7 1443.61   260.7 1448.18
#Mann= 3 ,-1,0
       0      .1       0    98.6    .045       0   107.1      .1       0
Bank Sta=98.6,107.1
XS Rating Curve= 0 ,0
Exp/Cntr(USF)=0,0
Exp/Cntr=0.3,0.1

Type RM Length L Ch R = 1 ,2166    ,170.2,172.8,169.3
XS GIS Cut Line= 3
2184531.81460545731141.0435959582184470.45575591731070.163545633
 2184291.6687633731114.595815986
#Sta/Elev= 30
       0 1445.33    13.8 1444.67    23.9  1444.4    47.4 1443.05    52.7 1442.54
    68.6 1438.91    73.9 1437.92    79.2 1436.65    84.5 1435.09    89.8 1434.05
   100.2  1433.5   112.6 1433.14   117.9 1432.61     125 1431.32   129.1  1430.8
   134.4 1431.25   137.3 1431.55   153.8 1431.12   157.9 1431.21     162 1431.46
   166.2 1432.04   170.7 1432.93   182.7 1433.85   211.5 1434.78   236.2  1436.3
   244.5 1437.25   248.6 1438.03     261 1440.96   269.2 1442.19     278 1443.98
#Mann= 3 ,-1,0
       0      .1       0     125    .045       0   134.4      .1       0
Bank Sta=125,134.4
XS Rating Curve= 0 ,0
Exp/Cntr(USF)=0,0
Exp/Cntr=0.3,0.1

Type RM Length L Ch R = 1 ,1993    ,219.7,221.3,222.5
XS GIS Cut Line= 2
2184507.05385527730967.0154108162184250.41022655731014.094252093
#Sta/Elev= 30
       0 1437.25    11.1 1436.32    15.1 1436.19    35.8    1436    47.7 1435.77
   108.7 1434.93   120.9 1434.84   133.1 1434.62   145.3 1434.56   165.8 1434.21
   173.7 1433.96   177.8 1433.75   181.9 1433.29   185.9 1432.06189.96321430.265
   194.1 1429.24198.06311430.102   202.2 1431.55   206.3 1433.22   210.3 1434.57
   214.4  1435.6     225 1438.54   230.7    1440   238.8 1442.41   242.9 1443.43
   246.9 1444.27   251.8 1445.43   255.1  1446.3   259.1 1446.77   260.9 1446.76
#Mann= 6 ,-1,0
       0      .1       0      30     .05       0     130      .1       0
189.9632    .045       0198.0631      .1       0     230     .05       0
Bank Sta=189.9632,198.0631
XS Rating Curve= 0 ,0
Exp/Cntr(USF)=0,0
Exp/Cntr=0.3,0.1

Type RM Length L Ch R = 1 ,1772    ,147.8,148.1,148
XS GIS Cut Line= 2
2184480.67794358 730803.747429872184224.06161063730770.869164383
#Sta/Elev= 30
       0 1434.05     4.5 1433.89    20.7 1433.69    28.7 1433.49    36.8    1433
    48.9 1432.51      61 1432.47   125.5 1430.72   129.6 1430.63   137.6 1430.64
   141.7 1430.44   145.7 1430.13   149.7 1429.67   153.7 1429.08   156.5 1428.39
   161.8 1426.88   165.8  1427.6   167.2 1428.51   169.9 1430.42   173.9 1432.92
   177.9 1434.28   182.6 1434.75     186 1435.03     190 1435.21   202.1 1435.18
   218.3 1435.59   234.4 1435.59   242.5 1435.84   250.5 1436.22   258.7 1436.41
#Mann= 4 ,-1,0
       0     .05       0   156.5    .045       0   167.2     .05       0
     200      .1       0
Bank Sta=156.5,167.2
XS Rating Curve= 0 ,0
Exp/Cntr(USF)=0,0
Exp/Cntr=0.3,0.1

Type RM Length L Ch R = 1 ,1624    ,184.8,185.1,184.7
XS GIS Cut Line= 2
2184496.80218072730660.4208774992184240.60596836730622.797657502
#Sta/Elev= 30
       0 1432.92      37 1432.16    73.4 1431.19    85.5  1430.7   105.7 1430.19
   113.8 1429.83   126.8 1429.62     134 1429.37   138.1 1429.09   146.2 1427.78
   150.2 1426.75   153.3 1425.49   154.3 1425.09   158.3  1424.2   162.4 1425.48
   166.4 1427.52   170.4 1429.31   174.5 1430.33   178.5  1431.1   182.6 1431.33
   190.7  1431.4   198.7 1431.84   206.8 1432.12     215 1431.91     219 1432.05
     227  1432.8   235.1 1432.79   246.6 1432.94   253.7 1432.79   258.9 1432.48
#Mann= 4 ,-1,0
       0     .05       0      20      .1       0   153.3    .045       0
   162.4      .1       0
Bank Sta=153.3,162.4
XS Rating Curve= 0 ,0
Exp/Cntr(USF)=0,0
Exp/Cntr=0.3,0.1

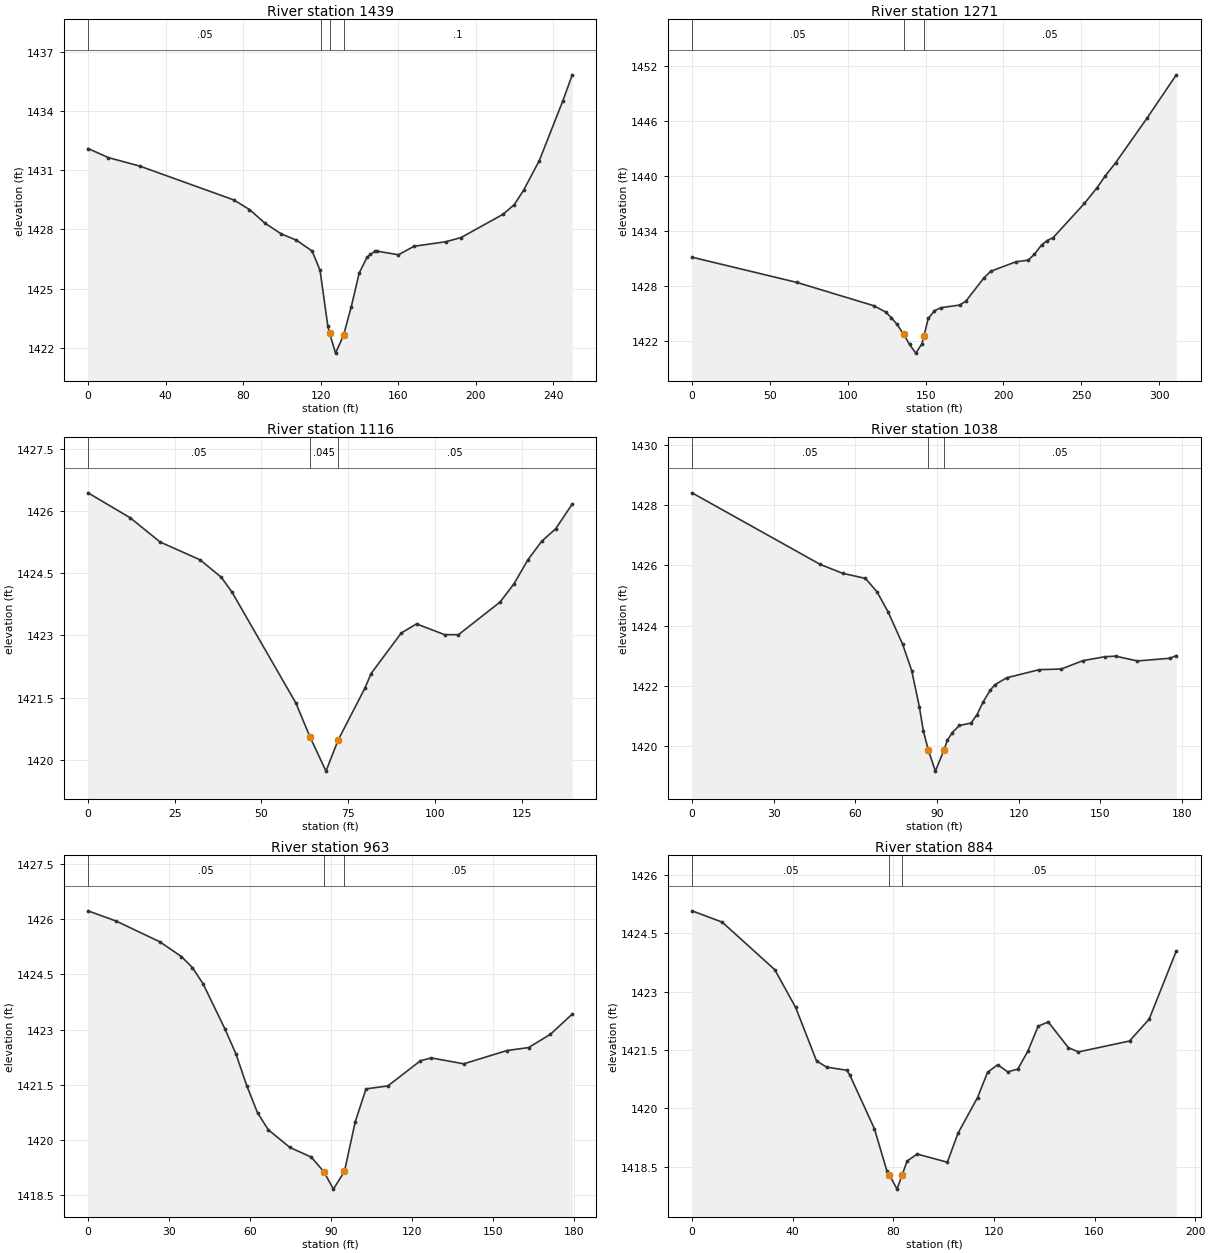
Type RM Length L Ch R = 1 ,1439    ,168.9,168.4,167.8
XS GIS Cut Line= 2
2184498.59376263730475.8879413212184251.35545979730440.056303228
#Sta/Elev= 30
       0  1432.1    10.5 1431.64    26.7 1431.21    75.1  1429.5    83.3 1429.01
    91.4 1428.31    99.8 1427.77   107.5 1427.46   115.6 1426.91   119.7 1425.93
   123.7 1423.11   124.6 1422.75   127.7 1421.74   131.8 1422.64   135.8 1424.09
   139.9  1425.8   143.9 1426.59   145.7 1426.74   147.9 1426.89   149.3  1426.9
   160.1 1426.72   168.2 1427.15   184.6 1427.38   192.4 1427.59   214.1 1428.77
   219.9 1429.26   224.7 1429.99   232.8 1431.49     245 1434.53   249.8 1435.83
#Mann= 4 ,-1,0
       0     .05       0     120      .1       0   124.6    .045       0
   131.8      .1       0
Bank Sta=124.6,131.8
XS Rating Curve= 0 ,0
Exp/Cntr(USF)=0,0
Exp/Cntr=0.3,0.1

Type RM Length L Ch R = 1 ,1271    ,152.7,154.7,155.9
XS GIS Cut Line= 2
2184543.38331024730303.8960784762184233.43964074730278.813931811
#Sta/Elev= 30
       0 1431.16    67.4  1428.4   116.9 1425.85   124.3 1425.17     128 1424.56
   131.6 1423.83   135.9 1422.75   139.7 1421.63   143.7 1420.68   147.7 1421.71
     149 1422.58   151.7 1424.47   155.7 1425.31   159.7 1425.64   171.8 1425.93
   175.8 1426.34   187.4 1428.88   191.8 1429.62   207.9 1430.65   215.9 1430.84
   219.9 1431.48   224.5  1432.5     228 1432.97     232 1433.31     252 1437.03
   260.1 1438.75   265.4 1440.04   272.1 1441.49   292.2 1446.35     311 1451.08
#Mann= 3 ,-1,0
       0     .05       0   135.9    .045       0     149     .05       0
Bank Sta=135.9,149
XS Rating Curve= 0 ,0
Exp/Cntr(USF)=0,0
Exp/Cntr=0.3,0.1

Type RM Length L Ch R = 1 ,1116    ,76.1,78.3,78.2
XS GIS Cut Line= 3
2184495.28618218730168.4890159442184406.95244937730130.887494547
2184363.38243252730130.887494547
#Sta/Elev= 22
       0 1426.45    12.1 1425.85    20.8 1425.26    32.3 1424.83    38.4 1424.41
    41.5 1424.05    59.9 1421.37      641420.546    68.6 1419.72    72.1 1420.47
    79.9 1421.74    81.6 1422.08    90.3 1423.06    94.7 1423.28   102.8 1423.02
   106.8 1423.02   118.8 1423.81   122.8 1424.25   126.8 1424.83   130.8 1425.28
   134.8 1425.58   139.6 1426.18
#Mann= 3 ,-1,0
       0     .05       0      64    .045       0    72.1     .05       0
Bank Sta=64,72.1
XS Rating Curve= 0 ,0
Exp/Cntr(USF)=0,0
Exp/Cntr=0.3,0.1

Type RM Length L Ch R = 1 ,1038    ,74.6,74.4,72.3
XS GIS Cut Line= 4
2184561.10690867730128.987381513 2184489.8322695730107.338542512
2184452.86271366730091.0186484962184389.91455103 730089.68641225
#Sta/Elev= 30
       0 1428.42      47 1426.04    55.3 1425.74    63.7 1425.57    67.9 1425.13
      72 1424.46    77.4 1423.37    80.7  1422.5    83.5  1421.3      85 1420.48
    86.81419.858    89.4 1419.15    92.6 1419.86    93.8 1420.18    95.6 1420.43
    98.2 1420.67   102.5 1420.75   104.7 1421.03   106.9 1421.45   109.6 1421.85
   111.3 1422.03   115.6 1422.26   127.6 1422.53   135.6 1422.55   143.6 1422.83
   151.6 1422.96   155.6 1422.98   163.6 1422.82   175.6 1422.91   177.9    1423
#Mann= 3 ,-1,0
       0     .05       0    86.8    .045       0    92.6     .05       0
Bank Sta=86.8,92.6
XS Rating Curve= 0 ,0
Exp/Cntr(USF)=0,0
Exp/Cntr=0.3,0.1

Type RM Length L Ch R = 1 ,963     ,76.8,79.1,79.1
XS GIS Cut Line= 6
2184550.63129494 730046.025385532184490.63052936 730039.70272421
2184461.08176523730041.8963005862184458.50108714730042.799537918
2184447.04317248730043.491323999  2184372.044933730049.696214315
#Sta/Elev= 26
       0 1426.22    10.5 1425.94    26.6 1425.38    34.6 1424.98    38.7 1424.68
    42.7 1424.23    50.7 1423.02    54.8 1422.34    58.8 1421.48    62.8 1420.74
    66.8 1420.28    74.8  1419.8    82.7 1419.54    87.4 1419.14    90.9 1418.67
      95 1419.15      99  1420.5     103 1421.39   111.1 1421.47   123.1 1422.15
   127.1 1422.23   139.2 1422.07   155.2 1422.43   163.2 1422.51   171.3 1422.87
   179.4 1423.42
#Mann= 3 ,-1,0
       0     .05       0    87.4    .045       0      95     .05       0
Bank Sta=87.4,95
XS Rating Curve= 0 ,0
Exp/Cntr(USF)=0,0
Exp/Cntr=0.3,0.1

Type RM Length L Ch R = 1 ,884     ,107,108.4,106.8
XS GIS Cut Line= 4
2184547.63514165729992.5321257492184502.06094222729978.797976624
2184426.46288291729976.9513274972184357.38108186729982.364540535
#Sta/Elev= 30
       0 1425.07      12 1424.78    32.9 1423.56    41.2 1422.59    49.5 1421.22
    53.5 1421.06    61.5 1420.98    62.7 1420.86    72.5 1419.48    77.5 1418.39
    78.4  1418.3    81.5 1417.93   83.521418.294    85.5 1418.65    89.5 1418.83
   101.5 1418.62   105.7 1419.36   113.5 1420.28   117.5 1420.93   121.5 1421.12
   125.5 1420.94   129.5 1421.01   133.5 1421.47   137.6 1422.11   141.6 1422.22
   149.6 1421.56   153.6 1421.45   173.9 1421.73   181.7 1422.29   192.5 1424.04
#Mann= 3 ,-1,0
       0     .05       0    78.4    .045       0   83.52     .05       0
Bank Sta=78.4,83.52
XS Rating Curve= 0 ,0
Exp/Cntr(USF)=0,0
Exp/Cntr=0.3,0.1

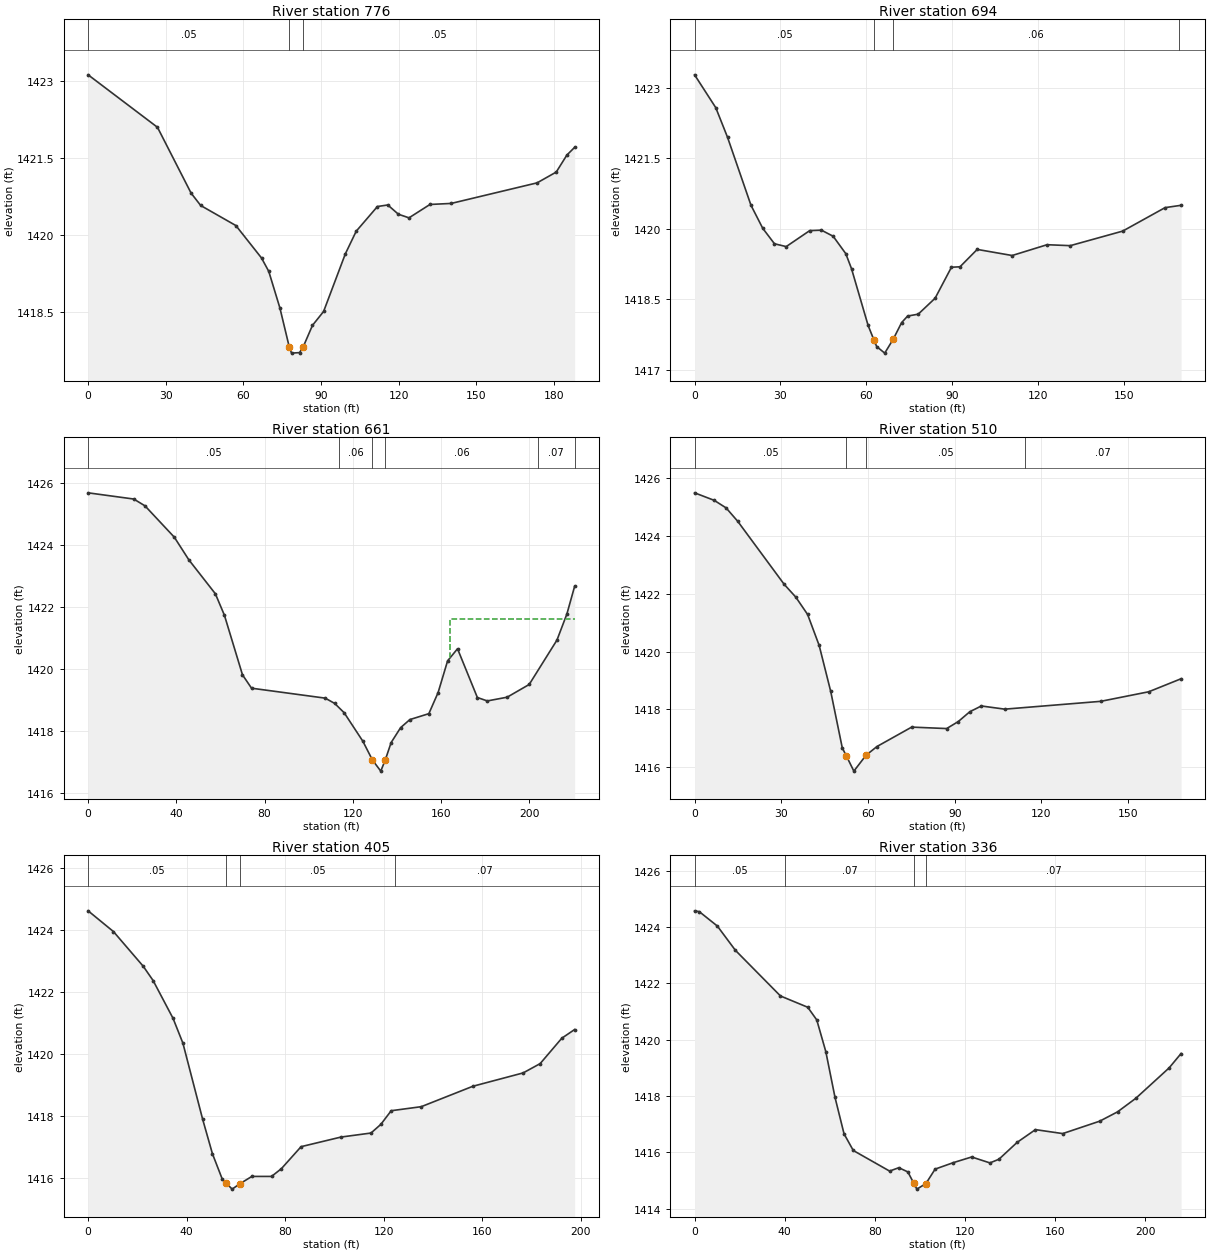
Type RM Length L Ch R = 1 ,776     ,81.1,81.9,79.6
XS GIS Cut Line= 4
2184544.99294105729917.1152016622184490.29955766 729894.63604409
2184448.17326237729908.9731445892184365.27262116729924.485518171
#Sta/Elev= 26
       0 1423.12    26.8  1422.1    39.8 1420.82    43.5 1420.58    57.1 1420.19
      67 1419.56    69.8  1419.3    74.1 1418.59    77.71417.836    78.6 1417.71
    81.7 1417.72   83.081417.828    86.7 1418.25      91 1418.52    99.4 1419.64
   103.6 1420.08   111.8 1420.56   115.8 1420.59   119.9 1420.41     124 1420.34
   132.1  1420.6   140.3 1420.62   173.5 1421.02   180.9 1421.23     185 1421.56
     188 1421.71
#Mann= 3 ,-1,0
       0     .05       0    77.7    .045       0   83.08     .05       0
Bank Sta=77.7,83.08
XS Rating Curve= 0 ,0
Exp/Cntr(USF)=0,0
Exp/Cntr=0.3,0.1

Type RM Length L Ch R = 1 ,694     ,30.2,32.6,35.5
XS GIS Cut Line= 6
2184539.33823058729841.7392300872184496.52111203  729831.6247366
2184487.87565882729830.0835224152184450.74256852729852.306028189
2184418.21776284729858.2576421482184378.77820838729868.718410377
#Sta/Elev= 30
       0 1423.28     7.4 1422.58    11.5 1421.95    19.7  1420.5    23.8 1420.01
    27.9 1419.68      32 1419.62    40.2 1419.96    44.3 1419.97    48.4 1419.84
    52.8 1419.47    54.8 1419.15    60.6 1417.94    62.7 1417.62    63.6 1417.49
    66.4 1417.35    69.4 1417.65    72.3    1418    74.4 1418.14    78.1 1418.18
      84 1418.52    89.7 1419.18    92.7 1419.19    98.7 1419.56   110.9 1419.43
   123.1 1419.66   131.2 1419.64   149.5 1419.95   164.3 1420.45   169.9  1420.5
#Mann= 4 ,-1,0
       0     .05       0    62.7    .045       0    69.4     .06       0
  169.12     .05       0
Bank Sta=62.7,69.4
XS Rating Curve= 0 ,0
Exp/Cntr(USF)=0,0
Exp/Cntr=0.3,0.1

Type RM Length L Ch R = 1 ,661     ,151,151,148.4
XS GIS Cut Line= 4
2184588.25985392 729844.237917072184497.00167106729822.256019007
2184431.38903593729797.9427075142184381.09711764729771.631041652
#Sta/Elev= 30
       0 1425.67    20.7 1425.47    25.8 1425.25    39.1 1424.24    45.7 1423.51
    57.7 1422.42    61.8 1421.73      70 1419.81    74.1 1419.38   107.5 1419.06
   111.8 1418.89   116.1 1418.59   124.6 1417.67   128.9 1417.07   132.7 1416.71
   134.81417.081   137.4 1417.63   141.7 1418.11   145.9 1418.37   154.5 1418.56
   158.7 1419.24     163 1420.26   167.5 1420.65   176.5 1419.08     181 1418.97
     190 1419.09     200  1419.5   212.6 1420.93   217.1 1421.77   220.6 1422.66
#Mann= 6 ,-1,0
       0     .05       0  113.87     .06       0   128.9    .045       0
   134.8     .06       0  203.84     .07       0   220.6     .05       0
#XS Ineff= 2 , 0
                          164.23         1421.61
Permanent Ineff=
       F       F
Bank Sta=128.9,134.8
XS Rating Curve= 0 ,0
Exp/Cntr(USF)=0,0
Exp/Cntr=0.3,0.1

Type RM Length L Ch R = 1 ,510     ,103.9,105.1,103
XS GIS Cut Line= 4
2184590.93437758729710.4683314362184564.61266055 729706.68452465
2184487.00989921729701.3555796652184425.39397282729684.369567526
#Sta/Elev= 23
       0 1425.48     6.8 1425.22    10.9 1424.96    14.9  1424.5      31 1422.32
      35 1421.88    39.1 1421.28    43.1 1420.21    47.1 1418.62    51.1 1416.67
    52.51416.398    55.1 1415.87    59.31416.417    63.1 1416.72    75.1 1417.39
    87.2 1417.34    91.2 1417.58    95.2 1417.92    99.2 1418.12   107.3 1418.01
   140.5 1418.28   157.1 1418.61   168.3 1419.06
#Mann= 4 ,-1,0
       0     .05       0    52.5    .045       0    59.3     .05       0
  114.38     .07       0
Bank Sta=52.5,59.3
XS Rating Curve= 0 ,0
Exp/Cntr(USF)=0,0
Exp/Cntr=0.3,0.1

Type RM Length L Ch R = 1 ,405     ,68.7,68.7,67.8
XS GIS Cut Line= 4
    2184602.4078729618.0783452252184569.22588245729613.808864358
2184507.95946249729612.575312278 2184407.0216894729632.579395193
#Sta/Elev= 26
       0 1424.63    10.3 1423.96    22.4 1422.84    26.4 1422.38    34.5 1421.16
    38.5 1420.36    46.5 1417.91    50.5 1416.79    54.5 1415.97    56.21415.834
    58.5 1415.65    61.61415.821    66.5 1416.06    74.5 1416.06    78.5 1416.31
    86.5 1417.02   102.7 1417.33   114.9 1417.46   118.9 1417.74   123.1 1418.18
   135.3 1418.31   156.3 1418.97   176.7  1419.4   183.6  1419.7   192.4 1420.52
   197.6  1420.8
#Mann= 4 ,-1,0
       0     .05       0    56.2    .045       0    61.6     .05       0
  124.73     .07       0
Bank Sta=56.2,61.6
XS Rating Curve= 0 ,0
Exp/Cntr(USF)=0,0
Exp/Cntr=0.3,0.1

Type RM Length L Ch R = 1 ,336     ,74.7,75.1,75
XS GIS Cut Line= 4
2184614.22768981729547.8823587592184570.04825051729545.963499968
2184441.34765018729564.4667811652184400.42217575729571.580906003
#Sta/Elev= 30
       0 1424.57     2.1 1424.54    10.1 1424.03    18.1 1423.17    38.1 1421.55
    50.2 1421.15    54.2  1420.7    58.2 1419.58    62.3 1417.95    66.3 1416.66
    70.4 1416.07    86.5 1415.34    90.6 1415.46    94.6 1415.31   97.29  1414.9
    98.6  1414.7   102.61414.896   106.7 1415.41   114.8 1415.64   122.9 1415.84
     131 1415.63     135 1415.76   143.1 1416.36   151.2 1416.81   163.3 1416.67
   179.7 1417.11   187.6 1417.44   195.7 1417.92   210.5    1419   215.8 1419.51
#Mann= 4 ,-1,0
       0     .05       0      40     .07       0   97.29    .045       0
   102.6     .07       0
Bank Sta=97.29,102.6
XS Rating Curve= 0 ,0
Exp/Cntr(USF)=0,0
Exp/Cntr=0.3,0.1

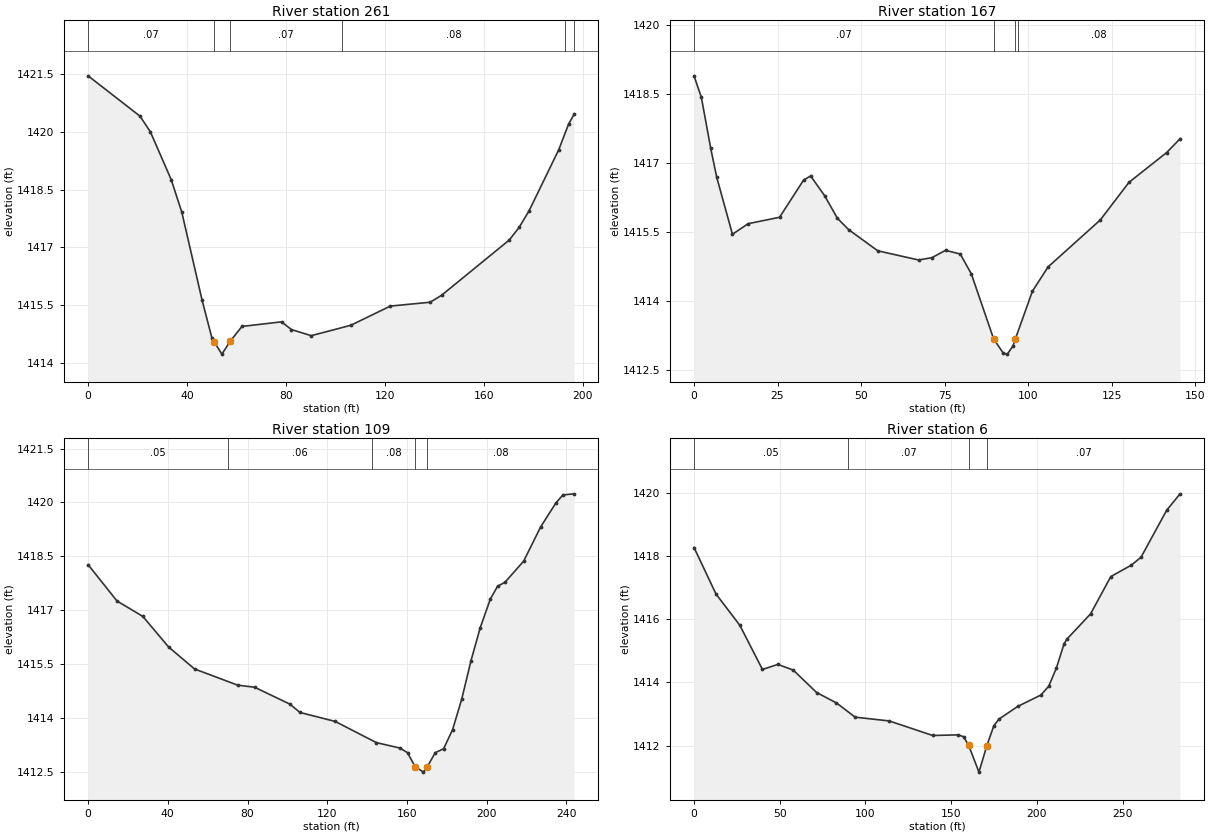
Type RM Length L Ch R = 1 ,261     ,89.7,94.3,96.8
XS GIS Cut Line= 3
2184580.03881771729494.0490289772184539.45304858729480.321489419
2184386.06271526729488.677383063
#Sta/Elev= 24
       0 1421.46      21 1420.41    25.2    1420    33.6 1418.76    37.9 1417.91
    46.1 1415.62    50.1 1414.63    51.11414.527    54.1 1414.22    57.4 1414.55
    62.2 1414.94    78.2 1415.06    82.2 1414.86    90.2  1414.7   106.2 1414.97
   122.2 1415.47   138.3 1415.57   142.9 1415.75   170.3 1417.19   174.3 1417.52
   178.3 1417.95   190.3 1419.54   194.3 1420.21   196.5 1420.46
#Mann= 6 ,-1,0
       0     .07       0    51.1    .045       0    57.4     .07       0
  102.84     .08       0  192.84     .07       0  196.46     .06       0
Bank Sta=51.1,57.4
XS Rating Curve= 0 ,0
Exp/Cntr(USF)=0,0
Exp/Cntr=0.3,0.1

Type RM Length L Ch R = 1 ,167     ,59.5,57.5,56.2
XS GIS Cut Line= 6
2184553.26172879729475.0187074422184535.38755916729445.746516589
2184538.34808415729422.0623166562184535.38755916729403.559035459
2184519.47473733729377.6544417832184498.38099676729345.828798124
#Sta/Elev= 29
       0  1418.9     2.2 1418.43       5 1417.32     6.8 1416.69    11.5 1415.45
    16.2 1415.68    25.6 1415.82    32.8 1416.63    34.9 1416.72    39.1 1416.29
    42.9  1415.8    46.3 1415.55      55 1415.09    67.2 1414.89    71.2 1414.94
    75.3  1415.1    79.7 1415.02      83 1414.59    89.7 1413.17    92.6 1412.86
    93.8 1412.84    95.5 1413.02    96.21413.172   101.3 1414.21     106 1414.74
   121.6 1415.76   130.2 1416.58   141.5 1417.23   145.5 1417.53
#Mann= 4 ,-1,0
       0     .07       0    89.7    .045       0    96.2     .07       0
   96.91     .08       0
Bank Sta=89.7,96.2
XS Rating Curve= 0 ,0
Exp/Cntr(USF)=0,0
Exp/Cntr=0.3,0.1

Type RM Length L Ch R = 1 ,109     ,103.1,103.1,103.1
XS GIS Cut Line= 4
2184713.60030027729414.9650773032184627.81005274729379.938289852
2184538.46636301729332.2206373822184498.87086415729301.762561337
#Sta/Elev= 30
       0 1418.27    14.5 1417.26    27.5 1416.83    40.4 1415.98    53.4 1415.37
      75 1414.92    83.6 1414.86   101.3 1414.39   106.3 1414.16     124 1413.91
   144.7 1413.32   156.5 1413.17   160.3 1413.04  164.081412.654   168.3  1412.5
   170.11412.638   174.2 1413.04   178.4 1413.15   182.9 1413.68   187.5 1414.53
   192.1 1415.59   196.8 1416.52   201.9 1417.32   205.5 1417.67   209.2 1417.78
   218.6 1418.37   227.1 1419.32   234.8 1419.99   238.3 1420.21   243.9 1420.24
#Mann= 5 ,-1,0
       0     .05       0      70     .06       0  142.67     .08       0
  164.08    .045       0   170.1     .08       0
Bank Sta=164.08,170.1
XS Rating Curve= 0 ,0
Exp/Cntr(USF)=0,0
Exp/Cntr=0.3,0.1

Type RM Length L Ch R = 1 ,6       ,,,
XS GIS Cut Line= 2
2184755.51258423 729329.915403832184504.23892537729198.608503713
#Sta/Elev= 30
       0 1418.27    12.8  1416.8    26.7 1415.81    39.9 1414.41    48.9 1414.57
    57.9 1414.39    71.5 1413.68    83.1 1413.35      94  1412.9   113.9 1412.78
   139.2 1412.32   154.2 1412.34   157.2 1412.28   160.1 1412.02   166.2 1411.16
   170.8    1412   174.9 1412.63   177.9 1412.84   188.8 1413.24   202.3  1413.6
   206.9 1413.88   211.4 1414.46   215.9 1415.23   217.5 1415.37   231.3 1416.17
   243.1 1417.35     255 1417.71   260.7 1417.96   275.7 1419.45   283.5 1419.97
#Mann= 4 ,-1,0
       0     .05       0      90     .07       0   160.1    .045       0
   170.8     .07       0
Bank Sta=160.1,170.8
XS Rating Curve= 0 ,0
Exp/Cntr(USF)=0,0
Exp/Cntr=0.3,0.1
LCMann Table=0

Chan Stop Cuts=-1
Use User Specified Reach Order=0
Composite Channel Slope=5